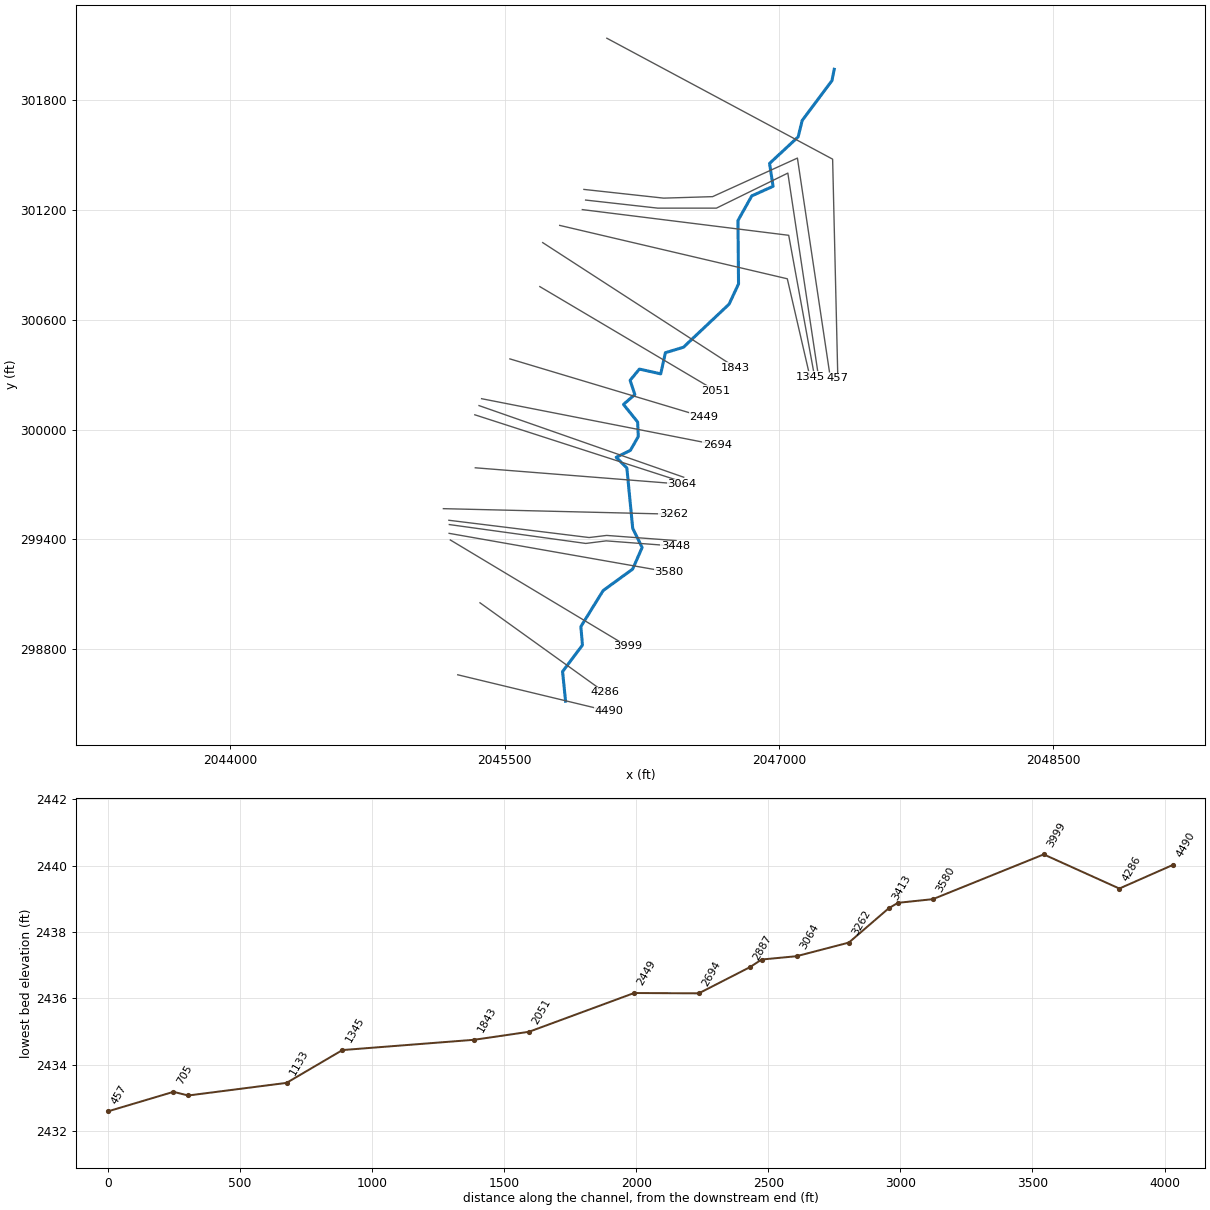
--- PATTSNCK.prj (project) ---

Proj Title=PATTSNCK
Current Plan=p01
Default Exp/Contr=0.3,0.1
English Units
Geom File=g01
Flow File=f01
Plan File=p01
Y Axis Title=Elevation
X Axis Title(PF)=Main Channel Distance
X Axis Title(XS)=Station
BEGIN DESCRIPTION:
Stream Name-  Patterson Creek
Flood Zone: Zone A
Greenbrier County, WV
County-Wide Study
WVDHSEM-2018-3, Flood Risk Project
HEC-RAS Version: 5.0.7
General Notes:
For the Hydrology regression was used.
END DESCRIPTION:
DSS File=dss
DSS Export Rating Curves= 0
DSS Export Rating Curve Sorted= 0
DSS Export Volume Flow Curves= 0
DXF Filename=..\H2c.
DXF OffsetX= 0
DXF OffsetY= 0
DXF ScaleX= 1
DXF ScaleY= 10

--- PATTSNCK.p01 (plan) ---

Plan Title=Floodplain
Program Version=5.07
Short Identifier=Floodplain
Geom File=g01
Flow File=f01
Subcritical Flow
K Sum by GR= 0
Std Step Tol= 0.01
Critical Tol= 0.01
Num of Std Step Trials= 20
Max Error Tol= 0.3
Flow Tol Ratio= 0.001
Split Flow NTrial= 30
Split Flow Tol= 0.02
Split Flow Ratio= 0.02
Log Output Level= 0
Friction Slope Method= 1
Unsteady Friction Slope Method= 2
Unsteady Bridges Friction Slope Method= 1
Parabolic Critical Depth
Global Vel Dist= 0 , 0 , 0
Global Log Level= 0
CheckData=True
Encroach Param=-1 ,0,0, 0
Computation Interval=1MIN
Output Interval=1HOUR
Instantaneous Interval=1HOUR
Mapping Interval=1HOUR
Computation Time Step Use Courant=        0
Computation Time Step Use Time Series=    0
Computation Time Step Count To Double=0
Computation Time Step Max Doubling=0
Computation Time Step Max Halving=0
Computation Time Step Residence Courant=0
Run HTab= 0
Run UNet= 0
Run Sediment= 0
Run PostProcess= 0
Run WQNet= 0
Run RASMapper= 0
UNET Theta= 1
UNET Theta Warmup= 1
UNET ZTol= 0.02
UNET ZSATol= 0.02
UNET MxIter= 20
UNET Max Iter WO Improvement= 0
UNET MaxInSteps= 0
UNET DtIC= 0
UNET DtMin= 0
UNET MaxCRTS= 20
UNET WFStab= 2
UNET SFStab= 1
UNET WFX= 1
UNET SFX= 1
UNET 1D Methodology=Finite Difference
UNET DSS MLevel= 4
UNET Pardiso=0
UNET DZMax Abort= 100
UNET Use Existing IB Tables=-1
UNET Froude Reduction=False
UNET Froude Limit= 0.8
UNET Froude Power= 4
UNET D1 Cores= 0
UNET D2 Coriolis=0
UNET D2 Cores= 0
UNET D2 Theta= 1
UNET D2 Theta Warmup= 1
UNET D2 Z Tol= 0.01
UNET D2 Volume Tol= 0.01
UNET D2 Max Iterations= 20
UNET D2 Equation= 0
UNET D2 RampUpFraction=0.1
UNET D2 TimeSlices= 1
UNET D2 BCVolumeCheck=0
UNET D1D2 MaxIter= 0
UNET D1D2 ZTol=0.01
UNET D1D2 QTol=0.1
UNET D1D2 MinQTol=1
DSS File=dss
Write IC File= 0
Write IC File at Fixed DateTime=0
Write IC File at Sim End=0
Echo Input=False
Echo Parameters=False
Echo Output=False
Write Detailed= 0
HDF Write Warmup=0
HDF Write Time Slices=0
HDF Flush=0
HDF Face Node Velocities=0
HDF Compression= 1
HDF Chunk Size= 1
HDF Spatial Parts= 1
HDF Use Max Rows=0
HDF Fixed Rows= 1
Calibration Method= 0
Calibration Iterations= 20
Calibration Max Change=0.05
Calibration Tolerance=0.2
Calibration Maximum=1.5
Calibration Minimum=0.5
Calibration Optimization Method= 1
WQ AD Non Conservative
WQ ULTIMATE=-1
WQ Max Comp Step=1HOUR
WQ Output Interval=15MIN
WQ Output Selected Increments= 0
WQ Output face flow=0
WQ Output face velocity=0
WQ Output face area=0
WQ Output face dispersion=0
WQ Output cell volume=0
WQ Output cell surface area=0
WQ Output cell continuity=0
WQ Output cumulative cell continuity=0
WQ Output face conc=0
WQ Output face dconc_dx=0
WQ Output face courant=0
WQ Output face peclet=0
WQ Output face adv mass=0
WQ Output face disp mass=0
WQ Output cell mass=0
WQ Output cell source sink temp=0
WQ Output nsm pathways=0
WQ Output nsm derived pathways=0
WQ Output MaxMinRange=-1
WQ Daily Max Min Mean=-1
WQ Daily Range=0
WQ Daily Time=0
WQ Create Restart=0
WQ Fixed Restart=0
WQ System Summary=0
WQ Write To DSS=0
WQ Use Fixed Temperature=0
Sorting and Armoring Iterations= 10
XS Update Threshold= 0.02
Bed Roughness Predictor= 0
Hydraulics Update Threshold= 0.02
Energy Slope Method= 1
Volume Change Method= 1
Sediment Retention Method= 0
XS Weighting Method= 0
Number of US Weighted Cross Sections= 1
Number of DS Weighted Cross Sections= 1
Upstream XS Weight=0
Main XS Weight=1
Downstream XS Weight=0
Number of DS XS's Weighted with US Boundary= 1
Upstream Boundary Weight= 1
Weight of XSs Associated with US Boundary= 0
Number of US XS's Weighted with DS Boundary= 1
Downstream Boundary Weight= 0.5
Weight of XSs Associated with DS Boundary= 0.5
Percentile Method= 0
Sediment Output Level= 3
Mass or Volume Output= 0
Output Increment Type= 1
Profile and TS Output Increment= 1
XS Output Flag= 0
XS Output Increment= 10
Write Gradation File= 0
Read Gradation Hotstart= 0
Write HDF5 File= 1
Write Binary Output= 1
Write DSS Sediment File= 0
SV Curve= 0
Specific Gage Flag= 0

--- PATTSNCK.f01 (steady flow) ---

Flow Title=H2c
Program Version=5.07
Number of Profiles= 6
Profile Names=f1p,f10p,f4p,f2p,f02p,f1pplus
River Rch & RM=PATTSNCK,Main            ,4490
     641     340     451     543     893     948
River Rch & RM=PATTSNCK,Main            ,761
     785     420     555     666    1090    1160
Boundary for River Rch & Prof#=PATTSNCK,Main            , 1
Up Type= 0
Dn Type= 3
Dn Slope=0.00237
Boundary for River Rch & Prof#=PATTSNCK,Main            , 2
Up Type= 0
Dn Type= 3
Dn Slope=0.00237
Boundary for River Rch & Prof#=PATTSNCK,Main            , 3
Up Type= 0
Dn Type= 3
Dn Slope=0.00237
Boundary for River Rch & Prof#=PATTSNCK,Main            , 4
Up Type= 0
Dn Type= 3
Dn Slope=0.00237
Boundary for River Rch & Prof#=PATTSNCK,Main            , 5
Up Type= 0
Dn Type= 3
Dn Slope=0.00237
Boundary for River Rch & Prof#=PATTSNCK,Main            , 6
Up Type= 0
Dn Type= 3
Dn Slope=0.00237
DSS Import GetInterval= 0
DSS Import GetPeak= 0
DSS Import FillOption= 0

--- PATTSNCK.g01 (geometry) ---

Geom Title=H2c
Program Version=5.07

River Reach=PATTSNCK        ,Main
Reach XY= 30
2045833.28885431298515.2680251582045816.97824277298677.272775759
2045925.72105545298821.7072766862045916.99723791298922.939849516
2046038.73312782299119.8522870812046200.09724294299237.181441385
2046252.07210663299355.507596036     2046200.533      299459.878
     2046168.482      299790.347     2046110.137      299848.229
     2046187.968      299886.286     2046231.113      299962.171
     2046227.514      300041.314     2046149.966       300137.48
     2046212.345      300191.409     2046186.309      300269.184
     2046237.128      300330.616     2046353.711      300304.445
      2046379.24      300420.159     2046477.696      300449.821
     2046727.447      300685.354     2046779.144       300796.17
     2046776.057      301142.559     2046851.663      301277.502
     2046967.923       301329.61     2046948.775      301454.751
     2047105.148      301599.903     2047127.025      301689.167
     2047289.931      301907.487     2047302.405      301969.232

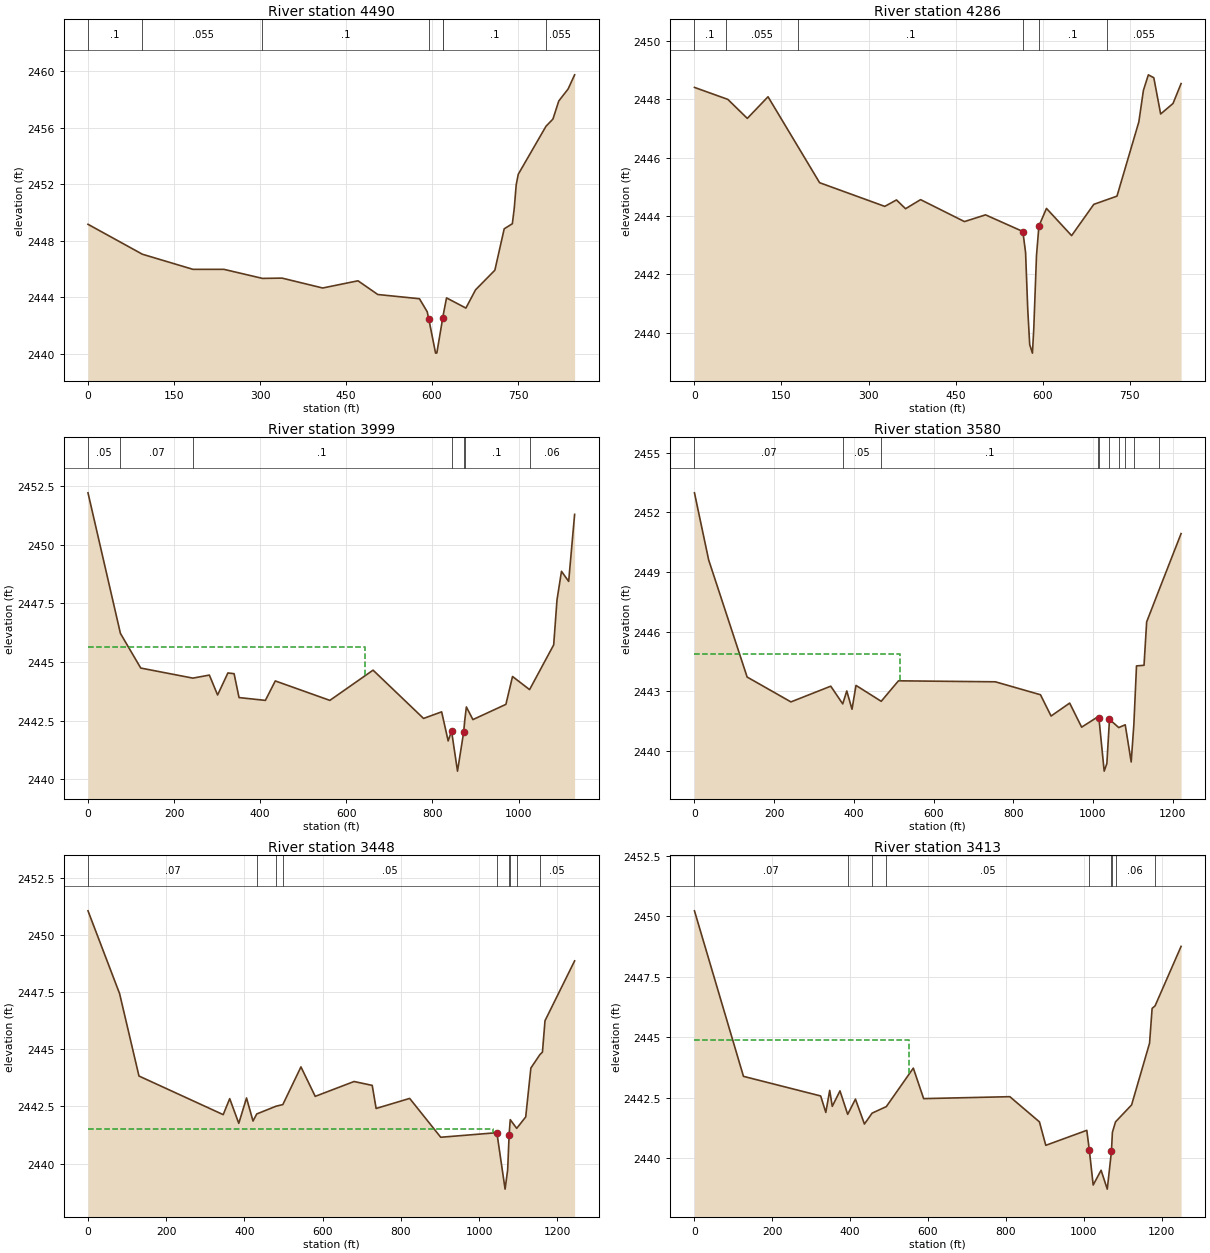
Type RM Length L Ch R = 1 ,4490    ,210.8,204.8,199.3
XS GIS Cut Line= 2
2045243.86786683298659.5737949512046068.98595311298460.851956289
#Sta/Elev= 30
       0 2449.15    94.9 2447.03   183.2 2445.96   237.2 2445.96   304.3 2445.32
   338.5 2445.34   409.3 2444.64   470.9 2445.15   505.4 2444.18   578.1 2443.88
   591.6 2442.96   594.3 2442.46   606.2 2440.03   608.4 2440.04   618.6  2442.5
   619.8 2442.78   625.3 2443.94   659.1 2443.22   675.9 2444.51   709.6  2445.9
   725.9 2448.83   740.1 2449.19   743.4 2450.27   746.8 2451.94   750.4 2452.69
   798.8 2456.09   810.9  2456.6   821.1 2457.88   837.4 2458.73   848.7 2459.73
#Mann= 7 ,-1 , 0
       0      .1       0    94.9    .055       0   304.3      .1       0
   594.3    .045       0   618.6    .045       0   619.8      .1       0
   798.8    .055       0
Bank Sta=594.3,618.6
XS Rating Curve= 0 ,0
Exp/Cntr(USF)=0,0
Exp/Cntr=0.3,0.1

Type RM Length L Ch R = 1 ,4286    ,279.7,286.2,283.8
XS GIS Cut Line= 2
2045365.50009265299053.024705925 2046046.8263973298563.963506766
#Sta/Elev= 30
       0  2448.4    57.5 2447.99    91.1 2447.34   126.8 2448.08   215.7 2445.14
     328 2444.33   348.2 2444.55   363.8 2444.25   389.7 2444.56   465.3 2443.81
   501.7 2444.04     566 2443.47   570.7 2442.75   574.4 2440.82   577.8  2439.6
   582.5 2439.31   584.8 2440.14   589.5 2442.65   593.7 2443.66   606.7 2444.26
     650 2443.33   688.3  2444.4   728.2 2444.68   765.9 2447.22   773.8  2448.3
   782.3 2448.83   791.7 2448.73   803.5 2447.49   824.8 2447.85   838.7 2448.53
#Mann= 6 ,-1 , 0
       0      .1       0   53.92    .055       0  179.04      .1       0
     566    .045       0   593.7      .1       0  711.78    .055       0
Bank Sta=566,593.7
XS Rating Curve= 0 ,0
Exp/Cntr(USF)=0,0
Exp/Cntr=0.3,0.1

Type RM Length L Ch R = 1 ,3999    ,411.3,419.6,420.8
XS GIS Cut Line= 2
2045203.27761433299396.4824848942046172.28763551298814.843816717
#Sta/Elev= 30
       0 2452.22    75.3 2446.22   122.5 2444.74   243.6 2444.31   281.9 2444.44
     301 2443.59   324.9 2444.53   339.3  2444.5   350.8 2443.48     412 2443.36
     435 2444.19   561.7 2443.36   662.1 2444.65   779.3 2442.59   821.4 2442.87
   836.5 2441.63   844.4 2442.05   858.2 2440.34   872.5    2442     875  2442.5
   878.8 2443.08     894 2442.54   970.6 2443.19     986 2444.38  1025.6 2443.82
  1081.6 2445.73  1089.3 2447.65  1099.7 2448.87  1116.4 2448.44  1130.2  2451.3
#Mann= 7 ,-1 , 0
       0     .05       0    75.3     .07       0   243.6      .1       0
   844.4    .045       0   872.5    .045       0     875      .1       0
  1025.6     .06       0
#XS Ineff= 2 , 0
          643.51 2445.65
Permanent Ineff=
       F       F
Bank Sta=844.4,872.5
XS Rating Curve= 0 ,0
Exp/Cntr(USF)=0,0
Exp/Cntr=0.3,0.1

Type RM Length L Ch R = 1 ,3580    ,128.5,131.8,132
XS GIS Cut Line= 2
2045196.66860935299432.7407205182046399.49737514299221.024245301
#Sta/Elev= 30
       0 2452.98    35.6 2449.61   132.2 2443.72   242.1 2442.47   342.1 2443.26
   372.1 2442.37   382.3 2443.02   395.4  2442.1   405.4  2443.3   468.7  2442.5
     512 2443.53   755.2 2443.48   868.4 2442.83     895 2441.76   941.7 2442.41
   971.7  2441.2    1014 2441.74    1015 2441.68  1028.3 2438.99    1035 2439.37
  1041.6 2441.59  1064.9 2441.18  1081.1 2441.32  1096.1 2439.45  1102.8 2441.34
  1109.4 2444.28  1128.3 2444.31  1134.9 2446.49  1164.9 2448.04  1221.3 2450.93
#Mann= 10 ,-1 , 0
       0     .07       0   372.1     .05       0   468.7      .1       0
    1014     .05       0    1015    .045       0  1041.6    .045       0
  1064.9     .06       0  1081.1    .045       0  1102.8     .06       0
  1164.9     .05       0
#XS Ineff= 2 , 0
          515.38  2444.9
Permanent Ineff=
       F       F
Bank Sta=1015,1041.6
XS Rating Curve= 0 ,0
Exp/Cntr(USF)=0,0
Exp/Cntr=0.5,0.3

Type RM Length L Ch R = 1 ,3448    ,45.3,34.7,31.3
XS GIS Cut Line= 4
2045197.76250784299480.7221821482045943.87868662299377.522263948
2046055.41151747299391.6241161252046432.45733792299363.113826673
#Sta/Elev= 30
       0 2451.06    80.7 2447.44   130.3 2443.83   345.6 2442.14   362.2 2442.84
   385.4 2441.76   405.2 2442.87   421.8 2441.86   431.3 2442.17   480.8 2442.51
     498 2442.58   544.3 2444.23   580.8 2442.94   680.1 2443.59   726.5 2443.42
   736.4 2442.41   822.2 2442.85   901.6 2441.15  1045.1 2441.35  1066.1 2438.88
  1072.7 2439.73  1076.4 2441.27  1079.3 2441.92  1095.8 2441.54  1118.8 2442.04
    1132 2444.18  1155.2 2444.77  1161.6 2444.88  1168.1 2446.25  1243.8 2448.87
#Mann= 9 ,-1 , 0
       0     .07       0   431.3     .05       0   480.8     .07       0
     498     .05       0  1045.1    .045       0  1076.4    .045       0
  1079.3     .05       0  1095.8     .06       0  1155.2     .05       0
#XS Ineff= 2 , 0
         1035.36  2441.5 1081.77          2441.5
Permanent Ineff=
       F       F
Bank Sta=1045.1,1076.4
XS Rating Curve= 0 ,0
Exp/Cntr(USF)=0,0
Exp/Cntr=0.5,0.3

Type RM Length L Ch R = 1 ,3413    ,140.7,151.7,156.3
XS GIS Cut Line= 4
2045195.36407548299504.1990653862045962.10324342299409.790896834
2046058.06253253  299421.36667012046437.79232183299393.134855418
#Sta/Elev= 30
       0 2450.22   125.9 2443.38   324.2 2442.57   337.4 2441.89   347.4  2442.8
     354 2442.14   373.8 2442.78   393.6 2441.81   413.5 2442.44   436.6 2441.41
   456.3 2441.86   492.8 2442.13   562.2 2443.72   588.7 2442.46   810.1 2442.54
   886.1  2441.5   902.5 2440.53  1007.8 2441.15  1014.4 2440.32  1024.2 2438.89
  1044.5  2439.5  1060.4 2438.72  1071.1 2440.28  1073.6 2441.07  1081.6  2441.5
  1122.9  2442.2    1169 2444.75  1175.6 2446.19  1183.1 2446.29    1250 2448.75
#Mann= 9 ,-1 , 0
       0     .07       0   393.6     .05       0   456.3     .07       0
   492.8     .05       0  1014.4    .045       0  1071.1    .045       0
  1073.6     .05       0  1081.6     .06       0  1183.1     .05       0
#XS Ineff= 2 , 0
          552.19  2444.9
Permanent Ineff=
       F       F
Bank Sta=1014.4,1071.1
XS Rating Curve= 0 ,0
Exp/Cntr(USF)=0,0
Exp/Cntr=0.5,0.3

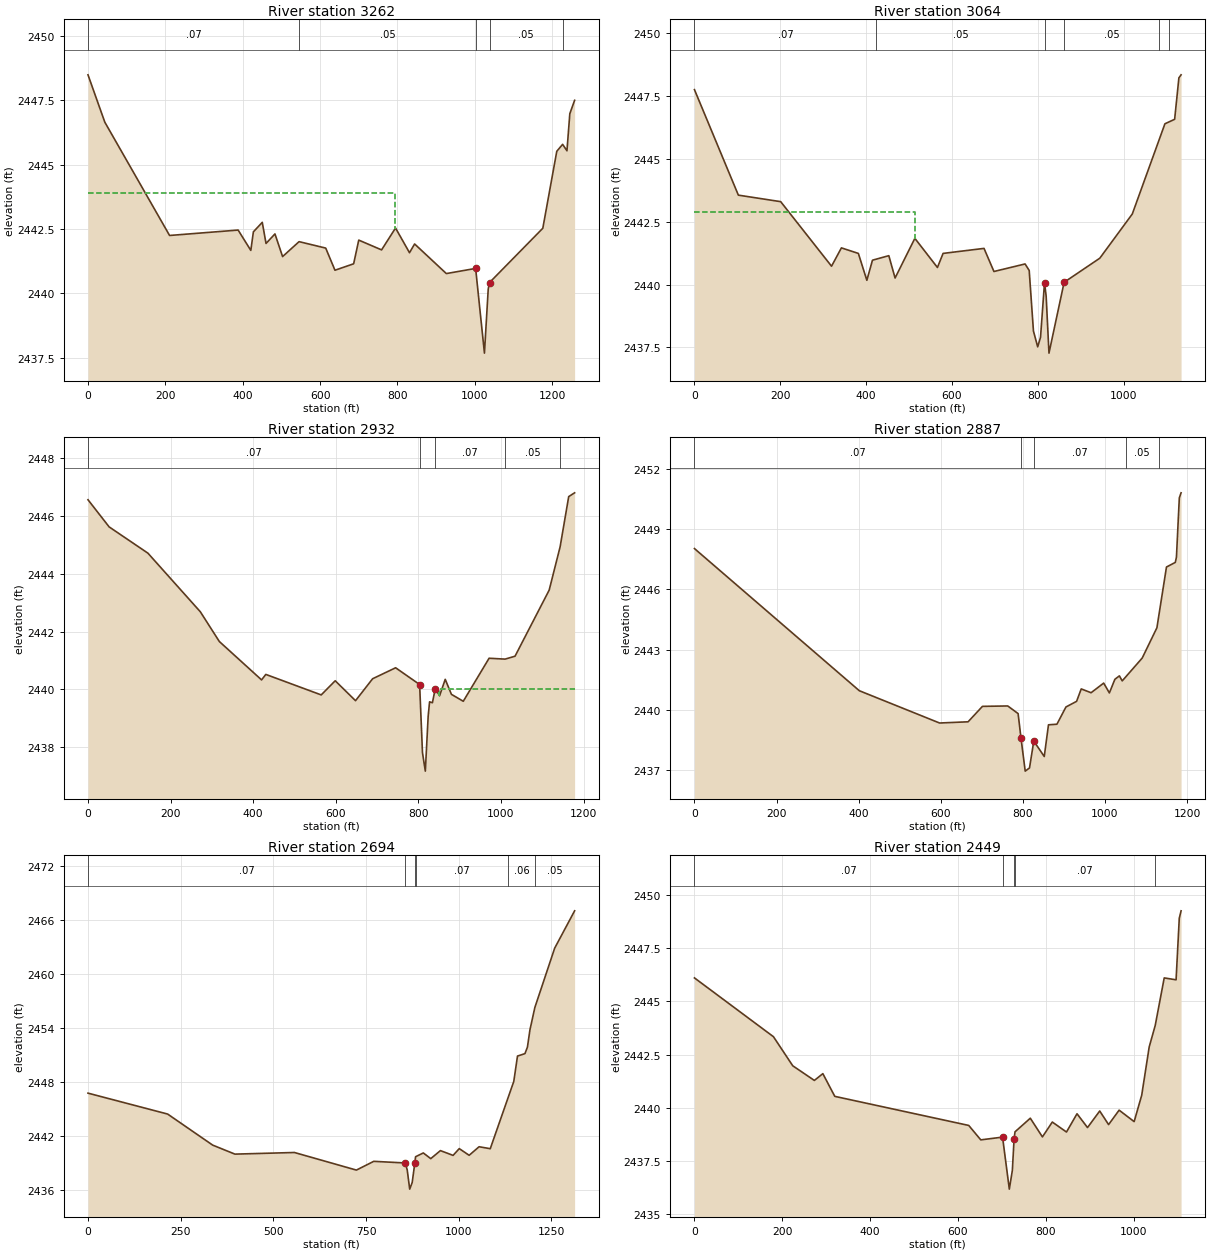
Type RM Length L Ch R = 1 ,3262    ,190.9,197.9,187.8
XS GIS Cut Line= 2
2045165.26012127299567.6808915352046422.76292187 299537.43568079
#Sta/Elev= 30
       0 2448.49    43.5 2446.65   210.9 2442.25   388.1 2442.46   420.9 2441.67
   427.5 2442.39   450.5 2442.76   460.2 2441.94   483.3 2442.31     503 2441.43
   545.6 2442.01   614.5 2441.76   638.4  2440.9   686.7 2441.15   699.9 2442.07
   758.9 2441.69     795 2442.54   831.1 2441.58   844.3 2441.92   926.3 2440.77
    1002 2440.97  1024.8 2437.68  1034.6 2440.17  1037.9 2440.42  1175.7 2442.53
  1211.8 2445.52  1226.9 2445.79  1238.1 2445.54  1245.5 2446.98  1257.9  2447.5
#Mann= 5 ,-1 , 0
       0     .07       0   545.6     .05       0    1002    .045       0
  1037.9     .05       0  1226.9    .055       0
#XS Ineff= 2 , 0
          793.15  2443.9
Permanent Ineff=
       F       F
Bank Sta=1002,1037.9
XS Rating Curve= 0 ,0
Exp/Cntr(USF)=0,0
Exp/Cntr=0.3,0.1

Type RM Length L Ch R = 1 ,3064    ,132.6,132,129.6
XS GIS Cut Line= 2
2045339.75172172299791.0301401152046470.45729266299701.457785216
#Sta/Elev= 30
       0 2447.76   102.3 2443.56     201  2443.3   319.5 2440.73   342.5 2441.46
     382 2441.24   401.8 2440.17   414.9 2440.97     453 2441.15   467.6 2440.26
   513.7 2441.84   566.3 2440.68   579.5 2441.24   674.9 2441.44     698 2440.52
   770.6 2440.82   780.2 2440.56   790.1 2438.15     800 2437.52   806.6  2437.9
   815.9 2440.08   819.7 2439.54   826.3 2437.27   861.6 2440.09   944.8 2441.05
  1020.5 2442.81  1096.5  2446.4  1119.2 2446.58  1129.1 2448.23  1134.2 2448.35
#Mann= 6 ,-1 , 0
       0     .07       0  424.19     .05       0   815.9    .045       0
   861.6     .05       0 1082.49    .055       0 1105.47     .06       0
#XS Ineff= 2 , 0
          513.47  2442.9
Permanent Ineff=
       F       F
Bank Sta=815.9,861.6
XS Rating Curve= 0 ,0
Exp/Cntr(USF)=0,0
Exp/Cntr=0.5,0.3

Type RM Length L Ch R = 1 ,2932    ,38.2,44.3,44.4
XS GIS Cut Line= 2
2045337.04899094300080.7916215522046458.33201545299718.547059011
#Sta/Elev= 30
       0 2446.57    51.2 2445.63   145.1 2444.72     272 2442.69     318 2441.66
   420.3 2440.33   430.6 2440.52   564.7 2439.81   598.6  2440.3   647.8 2439.61
   689.2 2440.37   744.9 2440.75     803 2440.17   809.9 2437.81   816.8 2437.17
   823.7 2439.07   827.1 2439.57     834 2439.54   840.9 2440.03   851.3 2439.78
     865 2440.35     880 2439.83   908.7 2439.59   971.2 2441.08  1009.9 2441.05
    1034 2441.15  1116.7 2443.44  1143.2 2444.94    1164 2446.68  1178.3 2446.81
#Mann= 5 ,-1 , 0
       0     .07       0     803    .045       0   840.9     .07       0
  1009.9     .05       0  1143.2     .06       0
#XS Ineff= 2 , 0
          775.46    2440     851            2440
Permanent Ineff=
       F       F
Bank Sta=803,840.9
XS Rating Curve= 0 ,0
Exp/Cntr(USF)=0,0
Exp/Cntr=0.5,0.3

Type RM Length L Ch R = 1 ,2887    ,193.7,193.8,189.4
XS GIS Cut Line= 2
 2045360.0818822300131.0452024832046479.27100751299739.486051066
#Sta/Elev= 30
       0 2448.04   401.7 2440.95   597.2 2439.34   666.7  2439.4   701.7 2440.17
   763.3 2440.19   788.6 2439.81   795.5 2438.61   805.9 2436.94   816.4  2437.1
   826.8 2438.44   852.3 2437.67   862.6 2439.25   883.2 2439.28   905.2 2440.14
   931.1 2440.42   942.4 2441.04   966.4 2440.85   997.1 2441.33    1011 2440.84
  1024.4 2441.52  1035.4 2441.69  1042.3 2441.44    1091 2442.58  1126.8 2444.09
  1150.1 2447.12  1171.6 2447.35  1174.4 2447.61  1181.4 2450.57  1185.7 2450.82
#Mann= 5 ,-1 , 0
       0     .07       0   795.5    .045       0   826.8     .07       0
 1051.52     .05       0 1130.68     .06       0
Bank Sta=795.5,826.8
XS Rating Curve= 0 ,0
Exp/Cntr(USF)=0,0
Exp/Cntr=0.5,0.3

Type RM Length L Ch R = 1 ,2694    ,237.8,244.6,233.6
XS GIS Cut Line= 2
 2045374.1950661300168.7727279472046662.41700525 299916.01123264
#Sta/Elev= 30
       0 2446.79   214.9 2444.47   336.3 2441.03   396.4 2440.03   556.9 2440.21
   724.1 2438.26   770.9 2439.23   855.8 2439.05   861.2 2438.28   867.9 2436.15
   874.6 2436.88   881.7 2439.04   883.7 2439.74   904.6 2440.16   924.7 2439.53
   950.8 2440.42   984.9 2439.89  1001.6 2440.64  1028.3  2439.9  1055.1 2440.85
  1085.2 2440.63  1132.5 2446.19  1148.7 2448.09  1158.7  2450.9  1178.8 2451.17
  1185.5 2451.89  1192.2 2453.79  1205.5 2456.28    1259 2462.86  1312.8    2467
#Mann= 6 ,-1 , 0
       0     .07       0   855.8    .045       0   881.7    .045       0
   883.7     .07       0  1132.5     .06       0  1205.5     .05       0
Bank Sta=855.8,881.7
XS Rating Curve= 0 ,0
Exp/Cntr(USF)=0,0
Exp/Cntr=0.3,0.1

Type RM Length L Ch R = 1 ,2449    ,396.1,398.3,381.7
XS GIS Cut Line= 2
2045529.04387502300386.2669735062046590.65077218300067.994294279
#Sta/Elev= 30
       0 2446.11   179.9 2443.34   223.9 2441.97   273.1 2441.28   292.4  2441.6
   319.6 2440.53   624.7 2439.16   652.1 2438.48   701.7 2438.61   717.1 2436.16
     724 2437.04     728 2438.54   730.1 2438.86   764.9  2439.5   792.5 2438.62
     815 2439.32   847.3 2438.85   871.3 2439.71   895.2 2439.06     923 2439.84
   943.2  2439.2   967.2 2439.88  1001.4 2439.34  1018.6 2440.58  1035.7 2442.86
  1049.4 2443.87  1069.9 2446.11  1096.9 2446.02  1104.2 2448.92  1108.3 2449.27
#Mann= 5 ,-1 , 0
       0     .07       0   701.7    .045       0     728    .045       0
   730.1     .07       0  1049.4     .06       0
Bank Sta=701.7,728
XS Rating Curve= 0 ,0
Exp/Cntr(USF)=0,0
Exp/Cntr=0.3,0.1

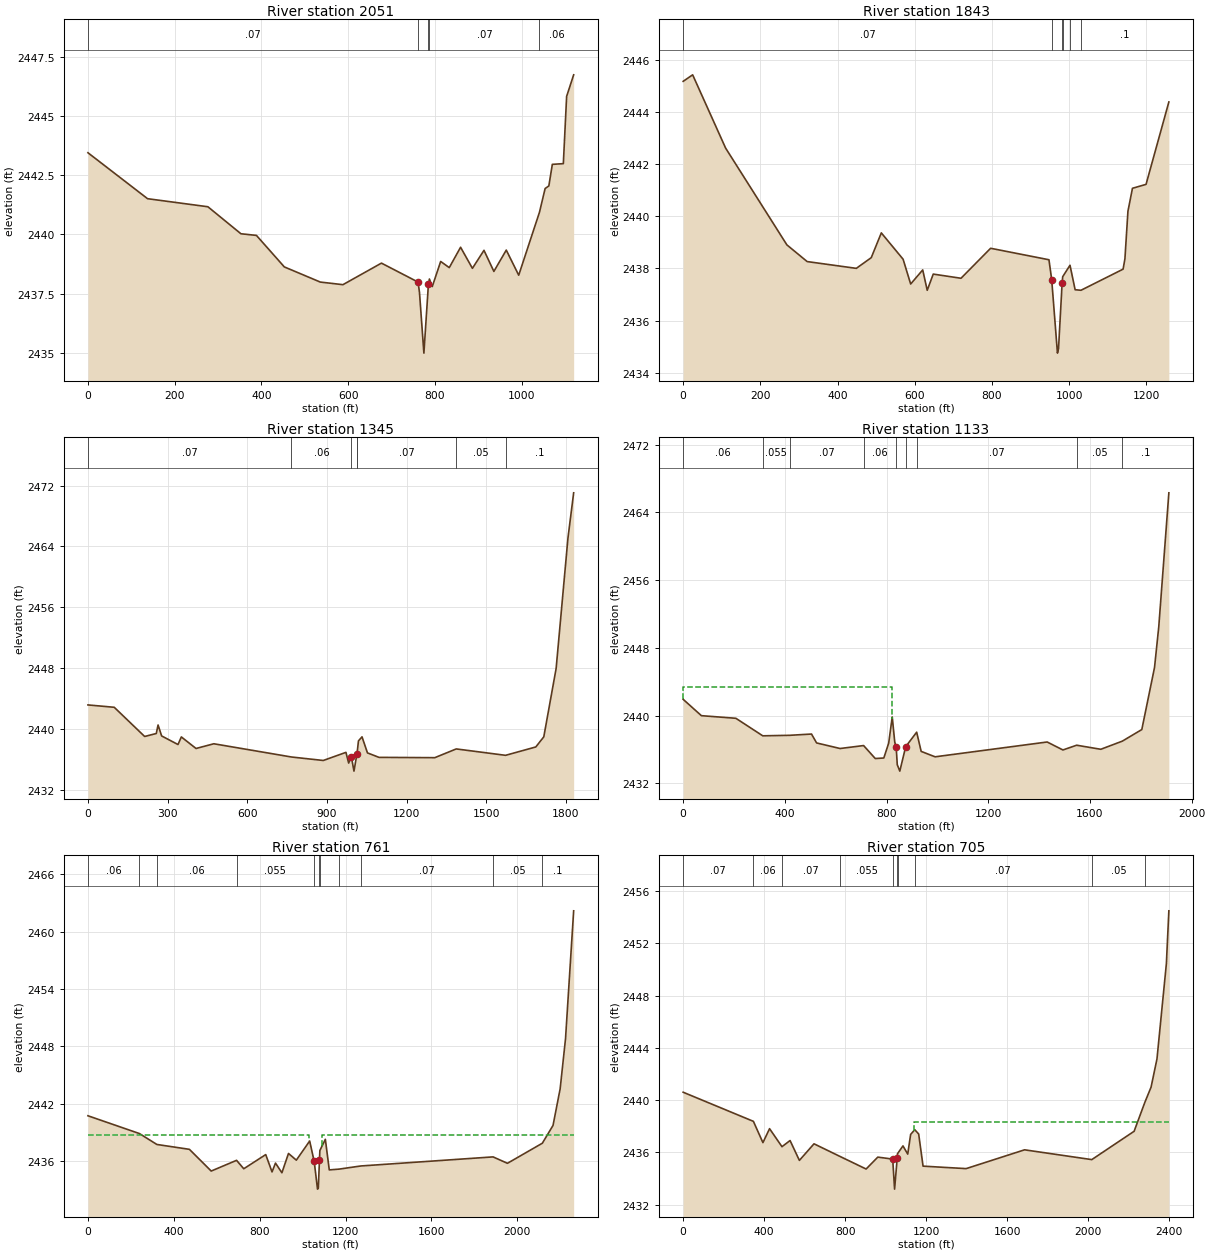
Type RM Length L Ch R = 1 ,2051    ,205.9,207.4,206
XS GIS Cut Line= 2
2045692.58973638300781.4576205592046656.38571102300210.595358423
#Sta/Elev= 30
       0 2443.45   137.5 2441.51   276.6 2441.17   352.8 2440.03   388.6 2439.96
   452.9 2438.63   535.9 2437.99   588.1 2437.88   676.9 2438.79   761.3 2437.99
   764.6 2437.56   774.8 2434.99   785.2 2437.89   787.5 2438.12   794.1  2437.8
   813.5 2438.86   833.3  2438.6   859.4 2439.46   886.7 2438.57   913.4 2439.33
   936.2 2438.44   964.8 2439.34   993.5 2438.28  1041.4 2440.94  1054.4 2441.94
    1063 2442.05    1071 2442.96  1096.4 2442.99    1104 2445.83  1120.2 2446.74
#Mann= 5 ,-1 , 0
       0     .07       0   761.3    .045       0   785.2    .045       0
   787.5     .07       0  1041.4     .06       0
Bank Sta=761.3,785.2
XS Rating Curve= 0 ,0
Exp/Cntr(USF)=0,0
Exp/Cntr=0.3,0.1

Type RM Length L Ch R = 1 ,1843    ,492.6,498.4,499.4
XS GIS Cut Line= 2
2045708.32389431301021.9157737452046764.30317902   300337.975809
#Sta/Elev= 30
       0 2445.17    24.6 2445.42     110 2442.61   268.7  2438.9   321.2 2438.26
   448.5    2438   487.2 2438.41   513.3 2439.36   569.7 2438.35   589.3  2437.4
   620.5 2437.94   632.2 2437.16   647.8 2437.78   719.7 2437.62   796.4 2438.77
   947.5 2438.33   954.6 2437.57   969.5 2434.75   972.3 2434.92   981.6 2437.44
   983.1 2437.68    1002 2438.12  1015.3 2437.18  1030.5 2437.16  1139.6 2437.97
  1144.3 2438.37  1152.1 2440.19  1163.8 2441.07    1199 2441.22  1258.1 2444.38
#Mann= 6 ,-1 , 0
       0     .07       0   954.6    .045       0   981.6    .045       0
   983.1     .06       0    1002     .07       0  1030.5      .1       0
Bank Sta=954.6,981.6
XS Rating Curve= 0 ,0
Exp/Cntr(USF)=0,0
Exp/Cntr=0.3,0.1

Type RM Length L Ch R = 1 ,1345    ,210.3,211.7,210.3
XS GIS Cut Line= 3
2045801.33535584301116.0027792332047045.82374395 300824.23340156
2047169.93502812 300287.00884293
#Sta/Elev= 30
       0 2443.15      99 2442.84   213.6    2439   257.4 2439.39   264.1 2440.51
   277.6 2439.07   339.2 2437.94   351.8 2438.94   407.1 2437.42   474.2 2438.04
   766.5  2436.3   886.4 2435.84   971.8 2436.91   982.1  2435.5     992 2436.36
  1002.1 2434.44  1012.92436.633  1014.7 2437.08    1019 2438.42  1032.4 2438.95
  1052.9 2436.84  1096.3 2436.25  1306.5 2436.21  1387.3 2437.36  1573.1 2436.52
    1687 2437.62  1717.1 2438.95  1763.6 2447.95  1808.2 2465.13  1829.6 2471.06
#Mann= 7 ,-1 , 0
       0     .07       0   766.5     .06       0     992    .045       0
  1012.9    .045       0  1014.7     .07       0  1387.3     .05       0
  1573.1      .1       0
Bank Sta=992,1012.9
XS Rating Curve= 0 ,0
Exp/Cntr(USF)=0,0
Exp/Cntr=0.3,0.1

Type RM Length L Ch R = 1 ,1133    ,363.1,372.1,368.5
XS GIS Cut Line= 3
2045924.99810696301202.3428051482047053.43747657 301061.88915046
2047192.68285349300301.547593361
#Sta/Elev= 30
       0 2441.93    71.7    2440   207.3 2439.69   313.1 2437.62   418.9 2437.68
   504.8 2437.83   524.7 2436.78   617.2 2436.12   709.6 2436.47   755.4 2434.94
   789.1    2435   808.3 2436.76   822.2 2439.85   832.1 2436.89   837.82436.242
     842 2434.21     852 2433.45   875.12436.333   918.3 2438.05     936 2435.78
   990.8 2435.14  1431.5 2436.89  1493.5 2435.95  1547.5 2436.51  1642.4 2436.03
    1727 2436.99  1803.7 2438.36  1853.7 2445.69  1870.4  2450.5  1910.1 2466.32
#Mann= 9 ,-1 , 0
       0     .06       0   313.1    .055       0   418.9     .07       0
   709.6     .06       0   837.8    .045       0   875.1     .06       0
   918.3     .07       0  1547.5     .05       0    1727      .1       0
#XS Ineff= 2 , 0
          821.35 2443.34
Permanent Ineff=
       F       F
Bank Sta=837.8,875.1
XS Rating Curve= 0 ,0
Exp/Cntr(USF)=0,0
Exp/Cntr=0.5,0.3

Type RM Length L Ch R = 1 ,761     ,56,55.8,55.4
XS GIS Cut Line= 5
2045942.93398893301254.5279713462046337.20318148 301210.37599789
2046658.26772632 301210.375997892047048.78164264 301401.92595855
2047214.26048676300304.739026383
#Sta/Elev= 30
       0 2440.74   239.8 2438.88     321 2437.74   472.7 2437.23   574.1 2434.96
   692.2 2436.08   725.8  2435.2   828.1 2436.68   857.4 2434.87   873.6 2435.79
   903.4 2434.78   934.1  2436.8   970.6  2436.1  1032.8  2438.1  1053.9 2435.96
  1069.3 2433.07    1073 2433.15  1078.4 2436.09  1080.3 2437.11  1105.8 2438.28
  1124.1 2435.08    1169 2435.16  1270.5 2435.49  1886.9 2436.44    1954 2435.77
  2116.5 2437.87  2166.3 2439.73  2199.5 2443.56  2224.6 2448.82  2262.4 2462.17
#Mann= 11 ,-1 , 0
       0     .06       0   239.8     .07       0     321     .06       0
   692.2    .055       0  1053.9    .045       0  1078.4    .045       0
  1080.3    .055       0    1169     .06       0  1270.5     .07       0
  1886.9     .05       0  2116.5      .1       0
#XS Ineff= 2 , 0
         1031.44  2438.7 1090.94          2438.7
Permanent Ineff=
       F       F
Bank Sta=1053.9,1078.4
XS Rating Curve= 0 ,0
Exp/Cntr(USF)=0,0
Exp/Cntr=0.5,0.3

Type RM Length L Ch R = 1 ,705     ,257.6,248.7,237.1
XS GIS Cut Line= 5
2045933.64879636301312.691838164 2046369.7749469301265.050032699
2046637.32873426301273.1929740532047101.11540848301483.989297074
2047276.31612884300315.377136455
#Sta/Elev= 30
       0  2440.6   346.7 2438.37   393.7 2436.74   426.5 2437.81   487.7 2436.43
   527.7  2436.9   573.7 2435.38   645.9 2436.65   775.9 2435.67   903.1 2434.72
   960.7 2435.63  1034.3 2435.48  1043.6 2433.18  1056.62435.552    1058 2435.89
  1085.1 2436.49  1108.5 2435.86  1122.9 2437.37  1143.3 2437.73  1162.5  2437.4
  1184.2 2434.94  1396.7 2434.75  1685.2 2436.19    2017 2435.44    2226 2437.61
  2279.1 2439.83  2309.7 2440.99  2338.8 2443.15  2385.2 2450.44  2397.5 2454.49
#Mann= 10 ,-1 , 0
       0     .07       0   346.7     .06       0   487.7     .07       0
   775.9    .055       0  1034.3    .045       0  1056.6    .045       0
    1058    .055       0  1143.3     .07       0    2017     .05       0
  2279.1      .1       0
#XS Ineff= 2 , 0
                         1139.44         2438.35
Permanent Ineff=
       F       F
Bank Sta=1034.3,1056.6
XS Rating Curve= 0 ,0
Exp/Cntr(USF)=0,0
Exp/Cntr=0.5,0.3

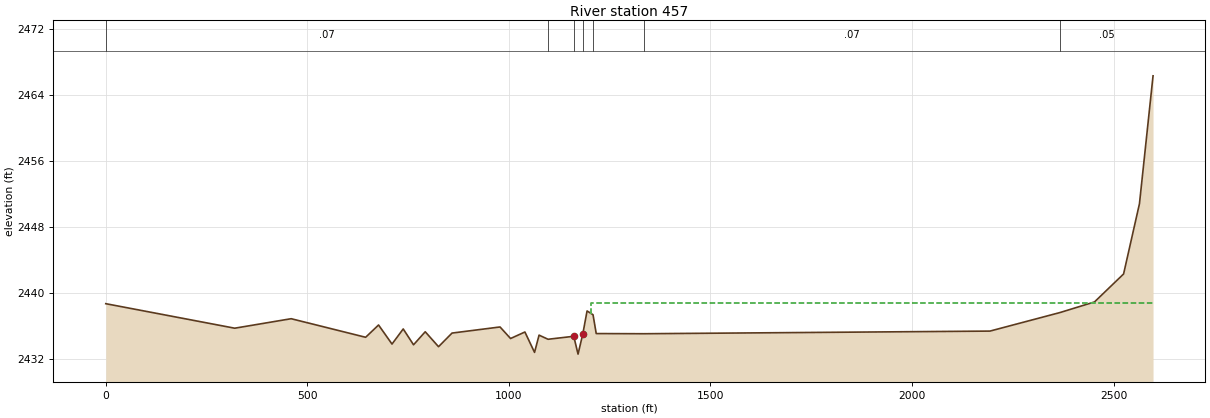
Type RM Length L Ch R = 1 ,457     ,456,456,456
XS GIS Cut Line= 3
2046059.09087873302139.1147510012047293.63698584  301478.0634667
2047322.09283582300280.728855729
#Sta/Elev= 30
       0  2438.7   319.9 2435.73   459.9 2436.88   644.7 2434.63   676.7 2436.12
   710.1 2433.81   737.9 2435.64   763.5 2433.72   792.5  2435.3   825.5 2433.49
     859 2435.14   978.1 2435.88  1004.2 2434.48  1039.8 2435.27  1063.7  2432.8
  1074.9 2434.89  1097.2 2434.39    1161 2434.75  1171.6 2432.59  1183.42435.028
    1194 2437.82  1208.8 2437.36  1216.7 2435.08  1335.1 2435.06  2193.5 2435.38
  2367.5 2437.63  2452.8 2438.91    2525  2442.3  2564.4 2450.81  2598.1  2466.3
#Mann= 7 ,-1 , 0
       0     .07       0  1097.2    .055       0    1161    .045       0
  1183.4    .055       0  1208.8     .06       0  1335.1     .07       0
  2367.5     .05       0
#XS Ineff= 2 , 0
                         1204.78         2438.75
Permanent Ineff=
       F       F
Bank Sta=1161,1183.4
XS Rating Curve= 0 ,0
Exp/Cntr(USF)=0,0
Exp/Cntr=0.3,0.1
LCMann Table=0

Chan Stop Cuts=-1
Use User Specified Reach Order=0
Composite Channel Slope=5